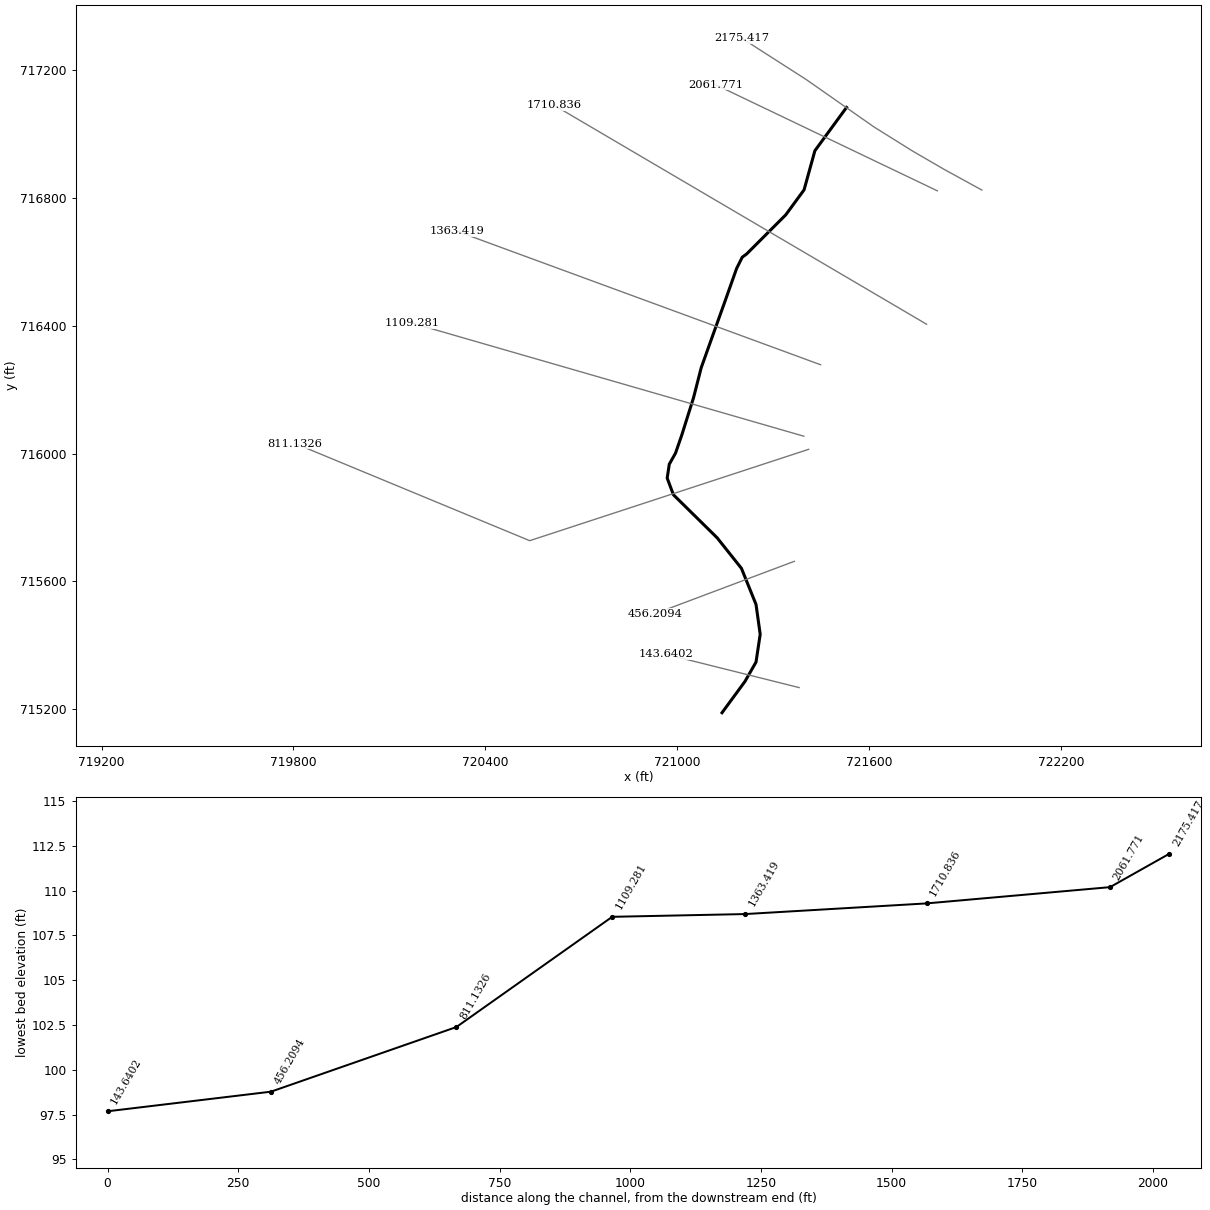
--- 4640_ras.prj (project) ---

Proj Title=4640
Current Plan=p01
Default Exp/Contr=0.3,0.1
English Units
Geom File=g01
Flow File=f01
Plan File=p01
Y Axis Title=Elevation
X Axis Title(PF)=Main Channel Distance
X Axis Title(XS)=Station
BEGIN DESCRIPTION:
RFD model 4640 exported to HEC-RAS
END DESCRIPTION:

--- 4640_ras.p01 (plan) ---

Plan Title=Plan 01
Program Version=4.10
Short Identifier=Plan 01
Geom File=g01
Flow File=f01
Subcritical Flow
Calc Critical at every XS
Secant Critical Depth

--- 4640_ras.f01 (steady flow) ---

Flow Title=Flow 01
Program Version=5.01
Number of Profiles= 6
Profile Names=10yr,25yr,50yr,100yr,100plus,500yr
River Rch & RM=4640,8,2175.417
   59.42  125.12  201.92  294.67  430.22 1151.94
Boundary for River Rch & Prof#=4640,8,1
Up Type= 0
Dn Type= 2
Boundary for River Rch & Prof#=4640,8,2
Up Type= 0
Dn Type= 2
Boundary for River Rch & Prof#=4640,8,2
Up Type= 0
Dn Type= 2
Boundary for River Rch & Prof#=4640,8,2
Up Type= 0
Dn Type= 2
Boundary for River Rch & Prof#=4640,8,2
Up Type= 0
Dn Type= 2
Boundary for River Rch & Prof#=4640,8,2
Up Type= 0
Dn Type= 2

--- 4640_ras.g01 (geometry) ---

Geom Title=4640
Program Version=4.10

River Reach=4640,8
Reach XY= 23
721529.319553018717082.233155936721430.361219645716946.816489279
721396.507052988716824.420655936721339.215386331716746.295655936
721216.819553018716623.899822608721203.247555673716613.899403527
 721185.56485796716578.534008145721148.672496855716474.367341474
 721107.43985796716359.349980354721074.887774676716268.204147026
721051.016246855716174.888174802721014.123885751716057.700674802
720994.592635751716001.277063712720975.061385781715966.554841474
720968.550969094715923.152063712720988.082219064715871.068730369
721124.800969094715736.520119235721200.755830228 715641.03400813
721246.328746885715528.186785907721259.349580199715434.870813683
721246.328746885715348.065258145721211.606524676 715287.30136925
721139.991941303715189.645119235

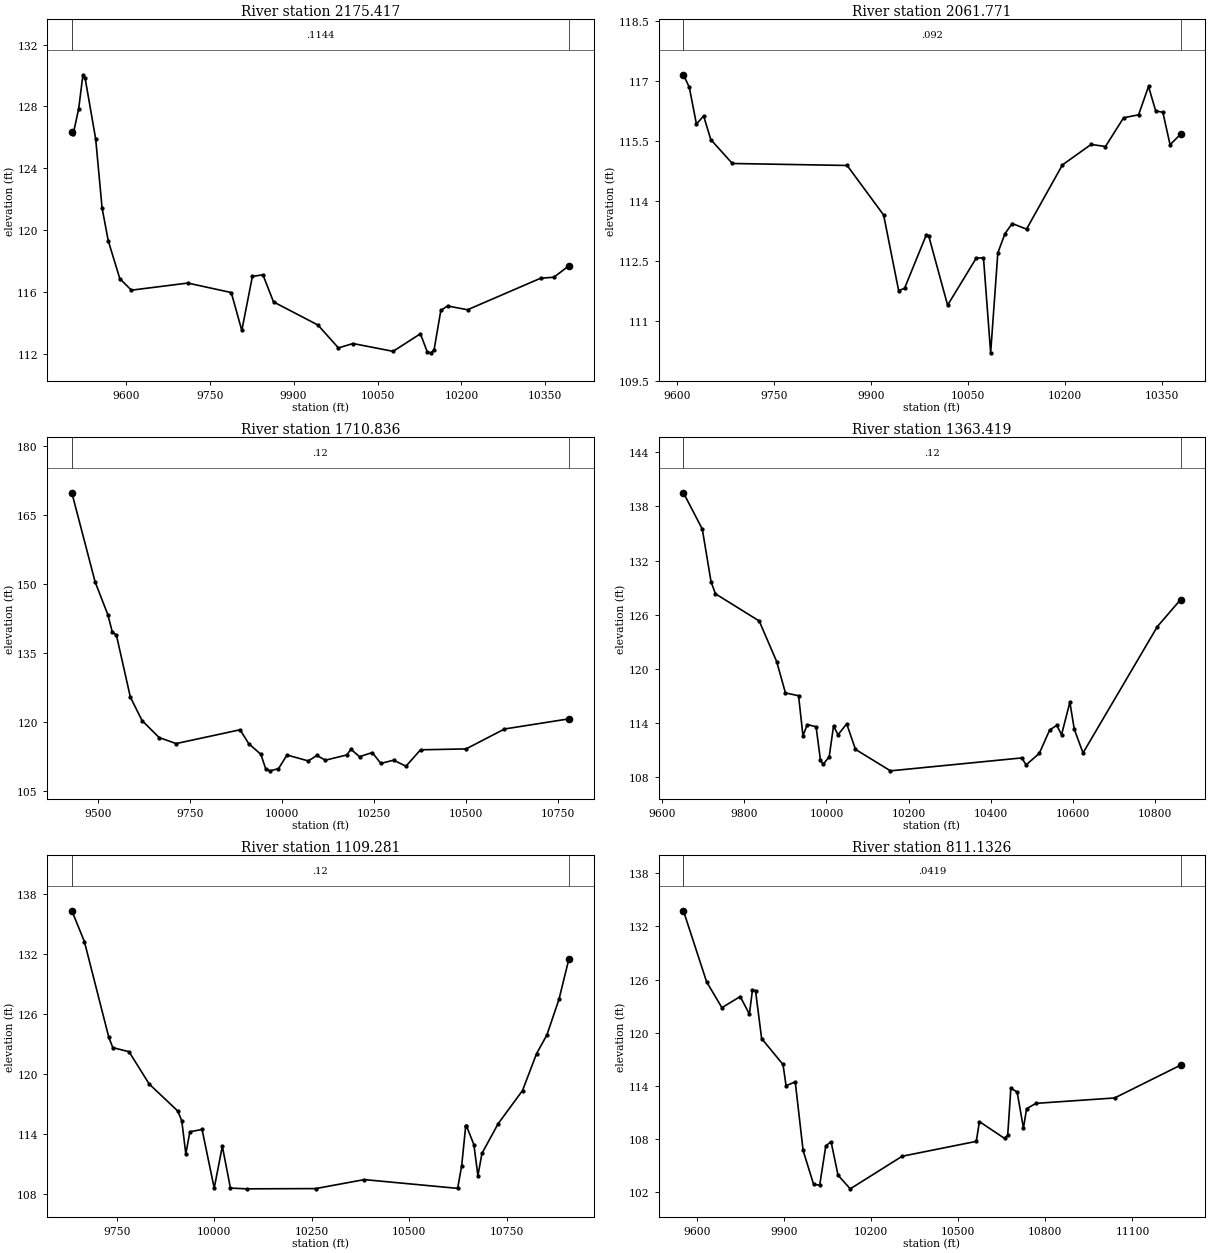
Type RM Length L Ch R = 1 ,2175.417,113.645100,113.645100,113.645100
XS GIS Cut Line= 6
721952.482073623716823.868807076721836.366577344716887.484182106
721736.842609716716945.158910837721615.782915208717020.761869342
721402.384411271717170.046057472721202.132335502717298.336348313
#Sta/Elev= 30
9503.736126.32869506.173126.21099516.025127.86499523.556130.04659527.279129.8673
9546.384125.88439557.799121.42859568.762119.31849589.503116.85539610.245116.1154
9710.961116.57479788.623115.96169807.502113.50769826.381117.00279845.259117.1109
9864.138 115.3579943.595113.85929980.156112.3797 10006.2112.663610077.85112.1587
 10126.7113.295710138.92112.120910145.54 112.06210151.13112.262310163.15114.8023
 10175.1115.095210210.94114.848210341.53116.888310365.16 116.95210392.16117.6926
#Mann= 3 , 0 , 0
9503.736  0.1144       09503.736  0.1144       010392.16  0.1144       0
#XS Ineff= 2 , 0
       0                               0
Bank Sta=9503.736,10392.16
Exp/Cntr=0.3,0.1

Type RM Length L Ch R = 1 ,2061.771,350.935400,350.935400,350.935400
XS GIS Cut Line= 2
721813.141897917716821.495663449721120.345924348717152.994812071
#Sta/Elev= 30
9610.372117.15569619.398116.84429630.484115.9204 9641.57 116.1269652.655115.5331
9685.913114.93519863.286114.88559919.677113.64469942.845111.75389951.973111.8093
 9985.23113.13389989.181113.130910018.49111.388410062.83112.568610073.92112.5734
   10085110.195310096.09112.696710107.17113.179610118.26113.432710140.43113.2924
10195.86114.8994 10240.2115.411610262.38115.360310290.37116.079110313.54116.1538
10328.89116.862810339.98116.250810351.06116.216610362.15115.404210378.39115.6664
#Mann= 3 , 0 , 0
9610.372   0.092       09610.372   0.092       010378.39   0.092       0
#XS Ineff= 2 , 0
       0                10202.48       0
Bank Sta=9610.372,10378.39
Exp/Cntr=0.3,0.1

Type RM Length L Ch R = 1 ,1710.836,347.417300,347.417300,347.417300
XS GIS Cut Line= 2
721779.619512111716404.328195512720613.785427541    717089.67475
#Sta/Elev= 30
9428.448169.85959491.806150.44019526.606143.25789538.206139.62249549.806138.8128
9587.633125.34899619.405120.24589665.805116.54169712.205115.22739886.203118.2321
9909.403115.22559942.818112.87039955.803109.71859967.403109.28759990.602109.7617
 10013.8112.7317 10071.8 111.448   10095112.6389 10118.2111.6092 10176.2112.7427
 10187.8113.9831   10211112.3611 10245.8113.2776   10269 110.906 10303.8111.6065
10337.47110.301410376.93113.8677   10501 114.065 10605.4118.403810780.81 120.612
#Mann= 3 , 0 , 0
9428.448    0.12       09428.448    0.12       010780.81    0.12       0
#XS Ineff= 2 , 0
       0                10115.22       0
Bank Sta=9428.448,10780.81
Exp/Cntr=0.3,0.1

Type RM Length L Ch R = 1 ,1363.419,254.137600,254.137600,254.137600
XS GIS Cut Line= 2
721448.120363474716277.688071311720312.083955228716694.855539247
#Sta/Elev= 30
9651.736139.51259697.672135.48939718.978129.6511 9729.63128.3168 9836.16125.3055
9878.771120.80339900.077117.32519932.036117.01999942.689112.59059953.342113.8231
9974.647 113.581  9985.3109.8821 9992.06109.407410006.61110.260710017.26113.7005
10027.91112.676910049.22113.901210070.52111.072310155.75108.692610475.33110.1249
10485.99109.356510517.95110.616210543.25113.217410560.56113.736610572.26112.7031
10592.52116.295810603.17113.315710624.48110.672410805.57124.688810861.95127.6655
#Mann= 3 , 0 , 0
9651.736    0.12       09651.736    0.12       010861.95    0.12       0
#XS Ineff= 2 , 0
       0                10025.98       0
Bank Sta=9651.736,10861.95
Exp/Cntr=0.3,0.1

Type RM Length L Ch R = 1 ,1109.281,298.148600,298.148600,298.148600
XS GIS Cut Line= 2
721395.974429935716054.205499172720170.544992864716408.052905023
#Sta/Elev= 30
9634.618136.28139666.858133.2074 9729.31123.67679739.718122.62889781.352122.2194
9833.395118.98379906.255116.31179916.663115.33049927.072 112.0289937.481114.2313
9968.706114.46439999.932108.610910020.75112.786310041.57 108.615 10083.2108.5394
10260.15108.564510385.05109.459910624.44108.586110634.85110.847510645.26114.8462
10646.78114.849610666.08 112.96110676.49109.8544 10686.9112.082710728.53115.0447
10790.97 118.34910827.01122.031810853.43123.886210884.66127.469110910.11131.5087
#Mann= 3 , 0 , 0
9634.618    0.12       09634.618    0.12       010910.11    0.12       0
#XS Ineff= 2 , 0
       0                10022.04       0
Bank Sta=9634.618,10910.11
Exp/Cntr=0.3,0.1

Type RM Length L Ch R = 1 ,811.1326,354.923200,354.923200,354.923200
XS GIS Cut Line= 3
721410.873268127716013.233694285720538.686101943715727.582903042
719805.179157555716031.402347475
#Sta/Elev= 30
9553.812133.76279633.651 125.7449686.265122.8275  9749.4124.08429780.968122.1003
9791.491124.82739802.014124.75459823.059119.34489896.718116.4179 9907.24114.0209
9938.808114.45589965.817106.728110001.94102.898810022.99102.801110044.03107.2318
 10062.2 107.70710086.13103.929210128.22102.3877 10307.1106.067510562.17107.7444
10572.99109.972710659.58 108.077 10670.4108.453810681.23 113.75810702.88113.3034
10724.52109.231810735.35111.434910767.82112.032911038.42112.641811265.52116.3432
#Mann= 3 , 0 , 0
9553.812  0.0419       09553.812  0.0419       011265.52  0.0419       0
#XS Ineff= 2 , 0
       0                10041.64       0
Bank Sta=9553.812,11265.52
Exp/Cntr=0.3,0.1

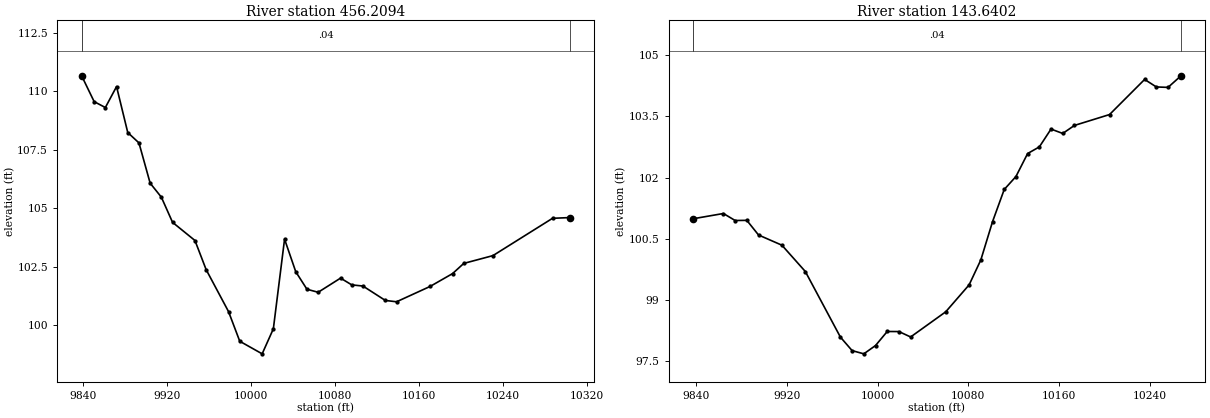
Type RM Length L Ch R = 1 ,456.2094,312.569200,312.569200,312.569200
XS GIS Cut Line= 2
  721366.1767537715663.110997975720930.385738045715499.223778427
#Sta/Elev= 30
9838.301110.65479850.242109.55029860.926 109.2999871.609110.19379882.293108.2305
9892.977107.78839903.661106.06779914.344105.47029925.028104.39539946.396103.6192
9957.079102.37399978.447100.58119989.13199.31642 10010.598.7789210021.1899.84842
10031.87103.676410042.55102.285610053.23101.536810063.92101.408410085.28 102.013
10095.97 101.72410106.65101.674310128.02 101.059 10138.7101.002410170.75101.6587
10192.12102.205910202.81102.641110230.66102.974210287.48104.567610303.89104.5984
#Mann= 3 , 0 , 0
9838.301    0.04       09838.301    0.04       010303.89    0.04       0
#XS Ineff= 2 , 0
       0                               0
Bank Sta=9838.301,10303.89
Exp/Cntr=0.3,0.1

Type RM Length L Ch R = 1 ,143.6402,0.000000,0.000000,0.000000
XS GIS Cut Line= 2
721381.075591832715268.291787237720963.908123851 715372.58365424
#Sta/Elev= 30
9837.354100.99359864.232 101.1239874.539100.95159884.847100.95529895.155100.5968
 9915.77100.34649936.38699.702249967.30998.094719977.61797.764149987.92597.68539
9998.233 97.888810008.5498.2327710018.8598.2310310029.1698.0984510060.0898.71487
10080.6999.37521   1009199.9851710101.31100.922310111.62 101.71210121.93102.0283
10132.23102.591910142.54102.754110152.85103.191110163.16103.083810173.46103.2802
10204.39103.546710235.31104.407110245.62104.222810255.93104.212310267.36104.4966
#Mann= 3 , 0 , 0
9837.354    0.04       09837.354    0.04       010267.36    0.04       0
#XS Ineff= 2 , 0
       0                               0
Bank Sta=9837.354,10267.36
Exp/Cntr=0.3,0.1